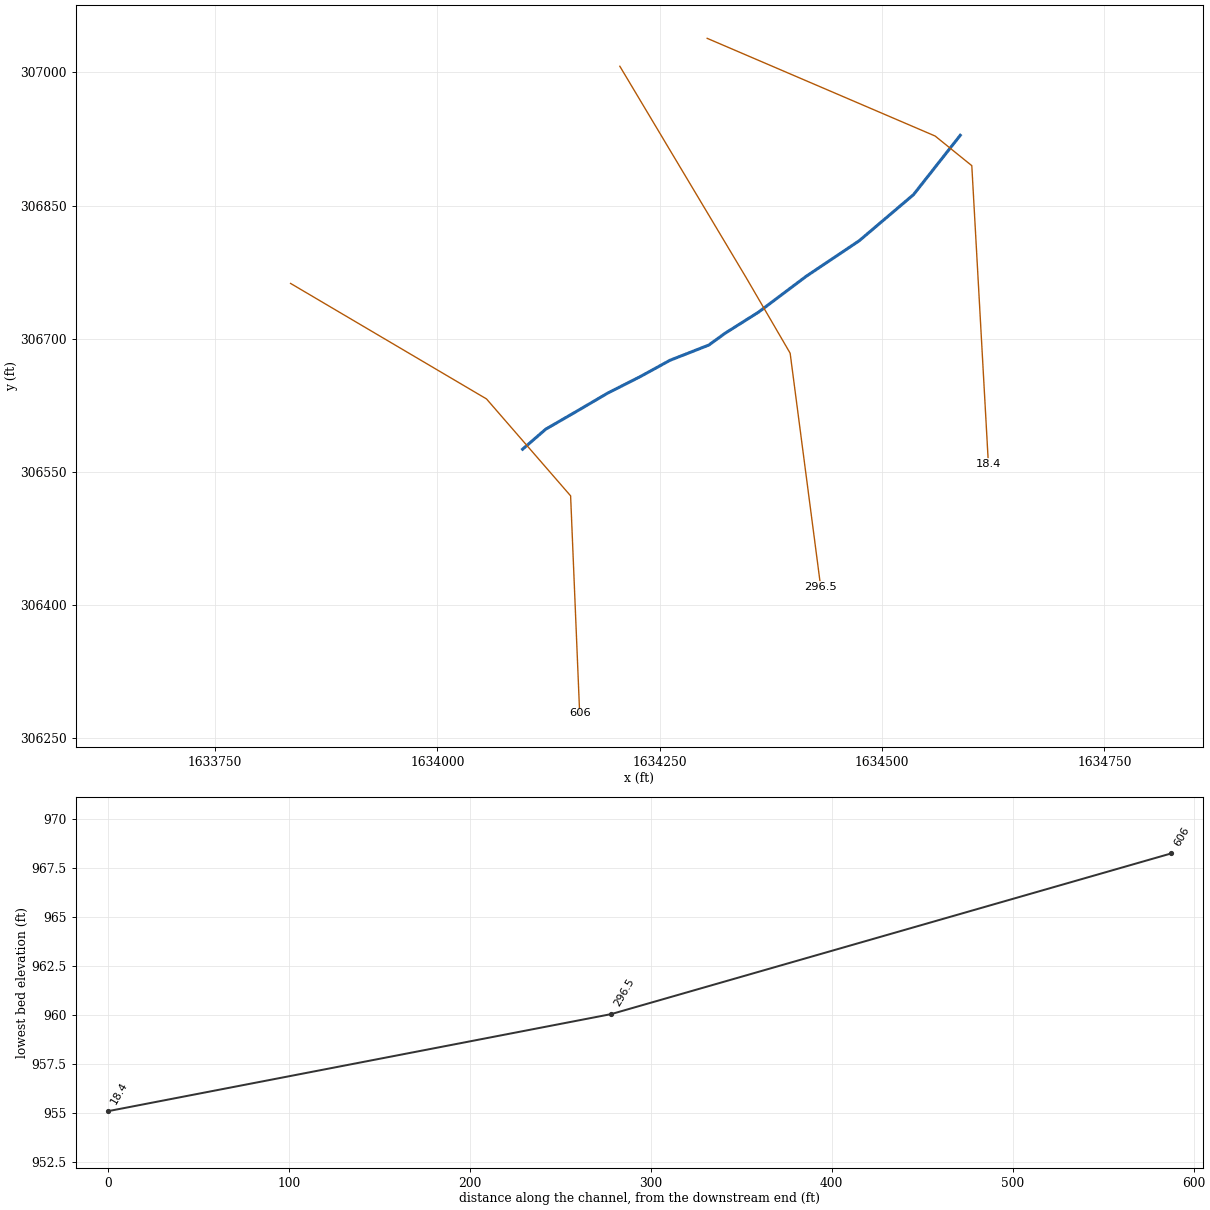
--- np12.prj (project) ---

Proj Title=np12
Current Plan=p01
Default Exp/Contr=0,0
English Units
Geom File=g01
Flow File=f01
Plan File=p01
BEGIN DESCRIPTION:
END DESCRIPTION:
DSS Export Rating Curves= 0
DSS Export Rating Curve Sorted= 0
DSS Export Volume Flow Curves= 0
DXF OffsetX= 0
DXF OffsetY= 0
DXF ScaleX= 0
DXF ScaleY= 0

--- np12.p01 (plan) ---

Plan Title=Floodplain
Program Version=4.00
Geom File=g01
Flow File=f01
K Sum by GR=0
Std Step Tol=0.01
Critical Tol=0.01
Num of Std Step Trials=20
Max Error Tol=0.3
Flow Tol Ratio=0.001
Split Flow NTrial=30
Split Flow Tol=0.02
Split Flow Ratio=0.02
Log Output Level=0
Friction Slope Method=1
Unsteady Friction Slope Method=2
Unsteady Bridges Friction Slope Method=1
Global Log Level=0
CheckData=False
Run HTab=0
Run UNet=0
Run PostProcess=0
UNET Theta=0
UNET Theta Warmup=0
UNET ZTol=0
UNET ZSATol=0
UNET MxIter=0
UNET MaxInSteps=0
UNET DtIC=0
UNET DtMin=0
UNET MaxCRTS=0
UNET WFStab=0
UNET SFStab=0
UNET WFX=0
UNET SFX=0
UNET DSS MLevel=0
UNET DZMax Abort=0
UNET Convert EG Bridges=0
UNET Use Existing IB Tables=0
UNET Froude Limit=0
UNET Froude Power=0
Write IC File=0
Echo Input=False
Echo Output=False
Write Detailed=0

--- np12.f01 (steady flow) ---

Flow Title=NFF Regression Equation
Program Version=4.00
Number of Profiles= 1
Profile Names=P100yr
River Rch & RM=np12,Main            ,606
     355
River Rch & RM=np12,Main            ,296.5
     358
Boundary for River Rch & Prof#=np12,Main            , 1
Up Type= 0
Dn Type= 3
Dn Slope=0.016
DSS Import GetInterval= 0
DSS Import GetPeak= 0
DSS Import FillOption= 0

--- np12.g01 (geometry) ---

Geom Title=USGS 10m DEM
Program Version=4.00

River Reach=np12     ,Main
Reach XY= 13
     1634095.691      306575.648     1634121.733      306598.218
     1634156.528      306618.358     1634191.336      306638.801
     1634228.354      306657.586     1634261.505      306675.819
     1634305.153      306692.947     1634323.386      306706.207
     1634360.956      306729.965     1634414.549      306770.298
     1634474.404      306810.516     1634535.318      306862.314
     1634587.915      306929.183

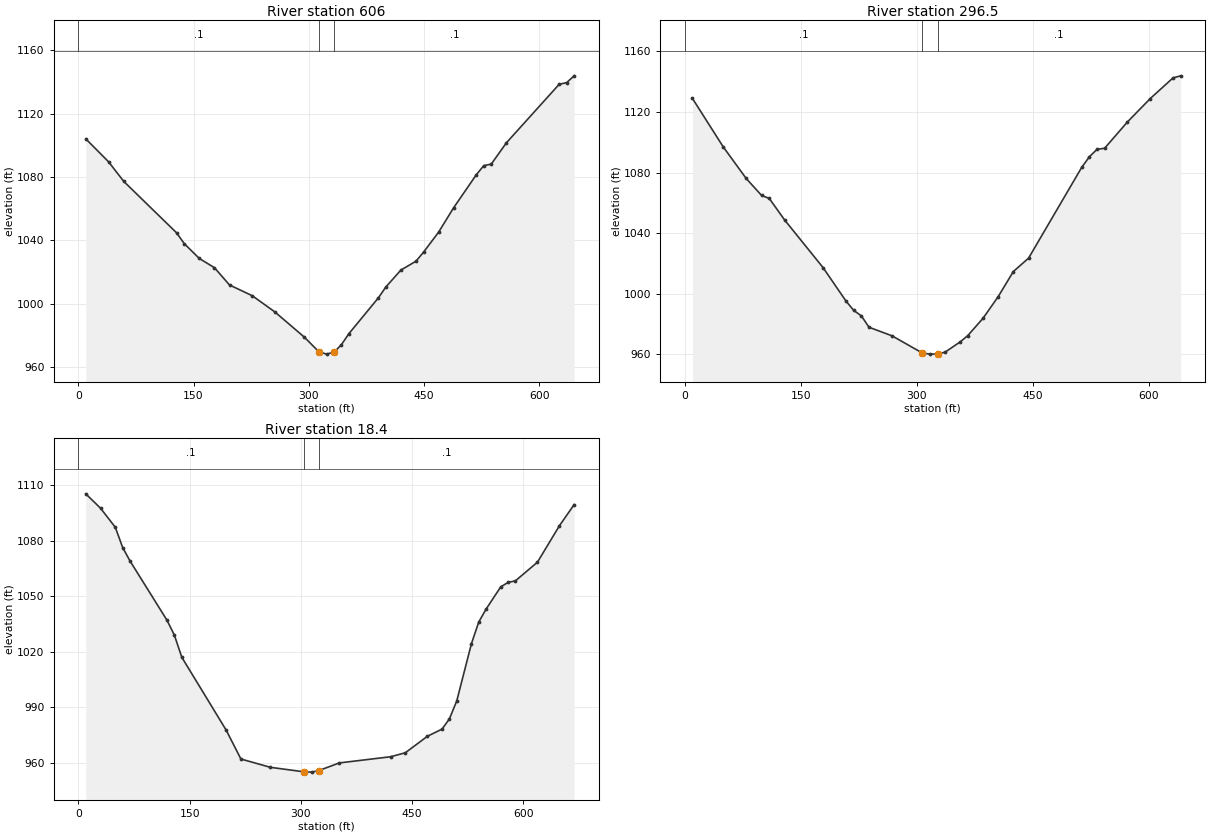
Type RM Length L Ch R = 1 ,606,314.2,309.5,304.8
XS GIS Cut Line= 4
     1633834.769      306762.394     1634055.118      306632.292
     1634149.715      306523.143     1634159.889      306278.151
#Sta/Elev= 30
     9.8 1104.09    39.4 1089.63    59.1 1077.30   127.9 1044.82   137.8 1038.04
   157.5 1028.63   177.2 1022.80   196.8 1011.90   226.4 1005.12   255.9  994.87
   294.4  978.89   313.3  969.66   323.3  968.24   333.3  969.61   342.6  974.27
   352.2  981.13   390.7 1003.82   400.3 1010.60   419.9 1021.30   439.6 1026.90
   449.4 1032.60   469.0 1045.21   488.6 1060.65   518.0 1081.39   527.8 1087.22
   537.6 1088.22   557.3 1101.64   625.9 1138.53   635.7 1139.63   645.5 1143.92
#Mann= 3 , 0 , 0
       0     0.1       0   313.3   0.045       0   333.3     0.1       0
Bank Sta=   313.3,   333.3
Exp/Cntr=0.3,0.1

Type RM Length L Ch R = 1 ,296.5,268.1,278.1,287.3
XS GIS Cut Line= 4
     1634205.072      307006.971     1634347.497      306768.287
     1634396.608      306683.815     1634430.987      306420.576
#Sta/Elev= 30
     9.9 1128.97    49.6 1097.05    79.4 1076.08    99.3 1064.89   109.2 1062.92
   129.0 1048.72   178.7 1017.25   208.5  995.04   218.4  988.94   228.3  985.30
   238.2  977.79   268.0  972.11     307  960.81   317.0  960.03     327  960.14
   336.6  961.35   356.1  968.12   365.9  972.29   385.5  983.65   405.2  998.01
   424.8 1014.61   444.5 1023.45   513.3 1083.50   523.1 1090.42   533.0 1095.36
   542.8 1096.05   572.3 1113.42   601.8 1128.89   631.3 1142.56   641.1 1143.92
#Mann= 3 , 0 , 0
       0     0.1       0     307   0.045       0     327     0.1       0
Bank Sta=     307,     327
Exp/Cntr=0.3,0.1

Type RM Length L Ch R = 1 ,18.4,19,18.4,18.7
XS GIS Cut Line= 4
     1634303.296      307038.403     1634559.660      306928.392
     1634600.914      306894.996     1634619.576      306559.071
#Sta/Elev= 30
    10.0 1105.33    29.9 1097.58    49.8 1087.30    59.8 1076.33    69.7 1069.06
   119.6 1037.04   129.5 1029.04   139.5 1017.08   199.3  977.77   219.2  962.15
   259.0  957.66   304.4  955.23   314.4  955.07   324.4  955.94   351.8  960.03
   421.1  963.38   440.9  965.53   470.6  974.42   490.4  978.31   500.3  983.81
   510.2  993.51   530.0 1024.41   539.9 1036.14   549.7 1043.05   569.5 1055.09
   579.4 1057.50   589.3 1058.35   619.0 1068.42   648.7 1088.14   668.5 1099.53
#Mann= 3 , 0 , 0
       0     0.1       0   304.4   0.045       0   324.4     0.1       0
Bank Sta=   304.4,   324.4
Exp/Cntr=0.3,0.1